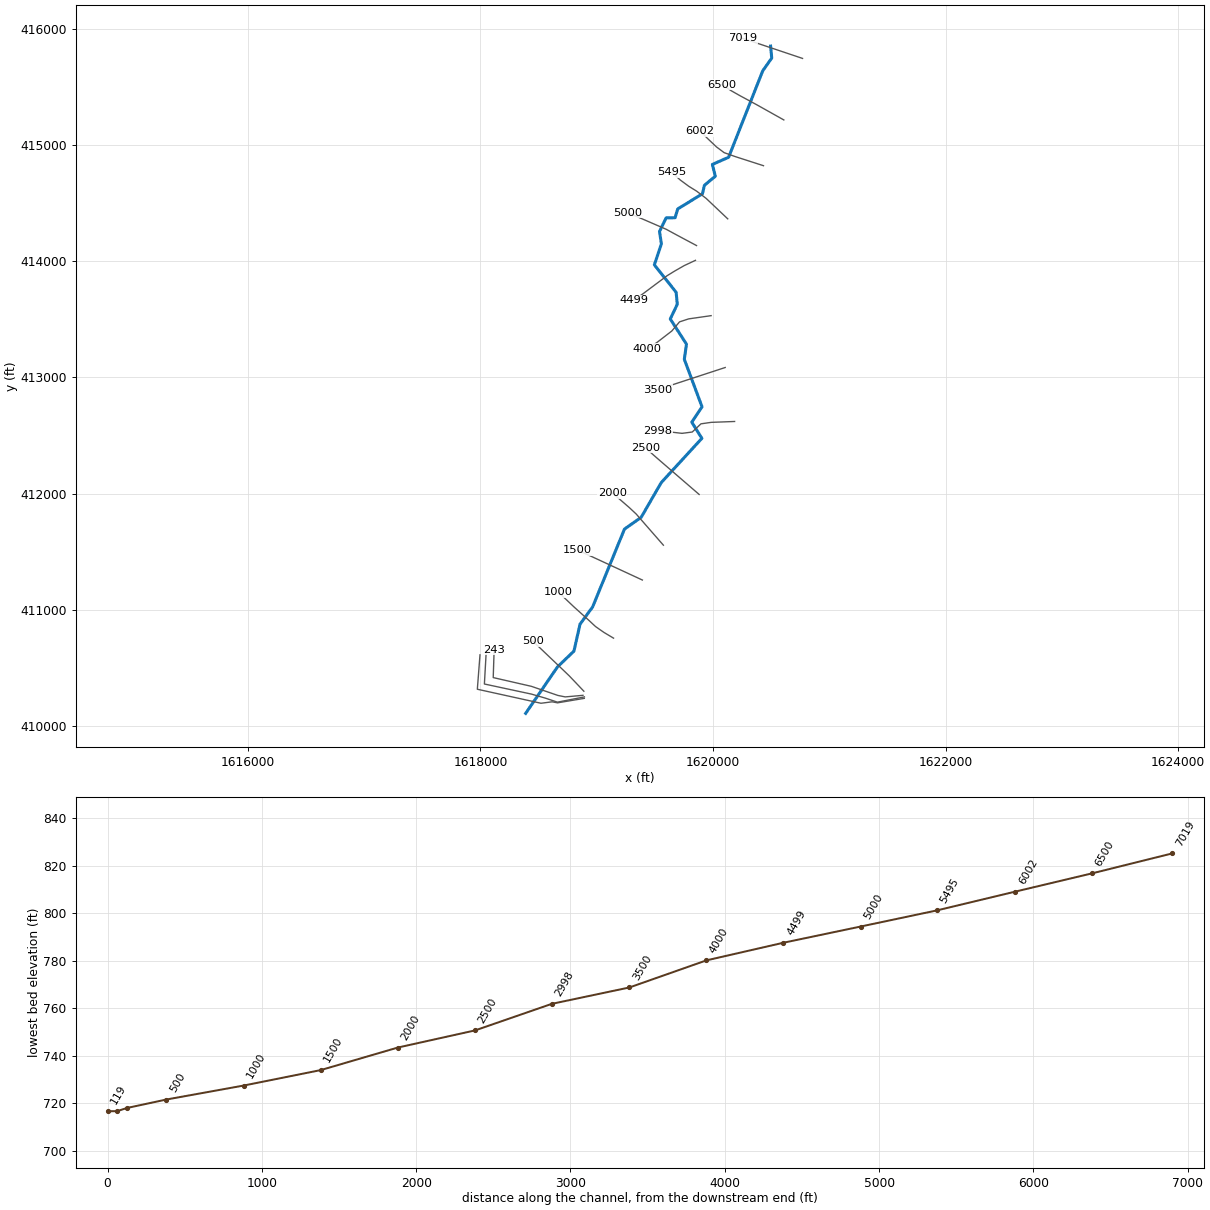
--- RUSHRN3.prj (project) ---

Proj Title=RUSHRN3
Current Plan=p01
Default Exp/Contr=0,0
English Units
Geom File=g01
Flow File=f01
Plan File=p01
BEGIN DESCRIPTION:
---------- MODELED AS PART OF WVEMD CTP PROGRAM, 2023----------
Stream Name: Rush Run III
Flood Zone:  AFH
Wetzel County, WV
HEC-RAS Version: RAS 6.3
Vertical Datum: NAVD88
Projection: NAD 1983 StatePlane West Virginia S FIPS 4702 (US Feet)
Terrain: 1-meter West Virginia FEMA R3 South Central (collected 2018-2020)
Land Use: 2019 NLCD
Hydrologic Method:
WV SIR2010-5033 regression equations
Additional Model Notes:
None
END DESCRIPTION:
DSS Export Rating Curves= 0
DSS Export Rating Curve Sorted= 0
DSS Export Volume Flow Curves= 0
DXF OffsetX= 0
DXF OffsetY= 0
DXF ScaleX= 0
DXF ScaleY= 0

--- RUSHRN3.p01 (plan) ---

Plan Title=Floodplain
Program Version=6.30
Short Identifier=Floodplain
Geom File=g01
Flow File=f01
Subcritical Flow
K Sum by GR= 0
Std Step Tol= 0.01
Critical Tol= 0.01
Num of Std Step Trials= 20
Max Error Tol= 0.3
Flow Tol Ratio= 0.001
Split Flow NTrial= 30
Split Flow Tol= 0.02
Split Flow Ratio= 0.02
Log Output Level= 0
Friction Slope Method= 1
Unsteady Friction Slope Method= 2
Unsteady Bridges Friction Slope Method= 1
Parabolic Critical Depth
Global Vel Dist= 0 , 0 , 0
Global Log Level= 0
CheckData=True
Encroach Param=-1 ,0,0, 0
Mapping Interval=1HOUR
Computation Time Step Use Courant=        0
Computation Time Step Use Time Series=    0
Computation Time Step Count To Double=0
Computation Time Step Max Doubling=0
Computation Time Step Max Halving=0
Computation Time Step Residence Courant=0
Run HTab= 0
Run UNet= 0
Run Sediment= 0
Run PostProcess= 0
Run WQNet= 0
Run RASMapper= 0
UNET Theta= 0
UNET Theta Warmup= 0
UNET ZTol= 0
UNET ZSATol= 0
UNET MxIter= 0
UNET Max Iter WO Improvement= 0
UNET MaxInSteps= 0
UNET DtIC= 0
UNET DtMin= 0
UNET MaxCRTS= 0
UNET WFStab= 0
UNET SFStab= 0
UNET WFX= 1
UNET SFX= 1
UNET Gravity=32.17405
UNET 1D Methodology=Finite Difference
UNET DSS MLevel= 1
UNET Pardiso=0
UNET DZMax Abort= 0
UNET Use Existing IB Tables= 0
UNET Froude Reduction=False
UNET Froude Limit= 0
UNET Froude Power= 0
UNET D1 Cores= 0
UNET WindReference=Eulerian
UNET WindDragFormulation=Hsu (1988)
UNET D2 Coriolis=0
UNET D2 Cores= 0
UNET D2 Theta= 1
UNET D2 Theta Warmup= 1
UNET D2 Z Tol= 0.01
UNET D2 Volume Tol= 0.01
UNET D2 Max Iterations= 20
UNET D2 Equation= 0
UNET D2 RampUpFraction=0.1
UNET D2 TimeSlices= 1
UNET D2 Turbulence Formulation=Non-Conservative (original)
UNET D2 Eddy Viscosity=0.3
UNET D2 Transverse Eddy Viscosity=0.1
UNET D2 Smagorinsky Mixing=0
UNET D2 BCVolumeCheck=0
UNET D2 Cores=0
UNET D2 SolverType=PARDISO (Direct)
UNET D2 Minimum Iterations= 3
UNET D2 Maximum Iterations= 30
UNET D2 Restart Number= 10
UNET D2 Relaxation Coeff=1.3
UNET D2 SOR Precondition Iterations= 10
UNET D2 ILUT Maximum Fill= 8
UNET D2 ILUT Tolerance=1E-08
UNET D2 Convergence Tolerance=0.00001
UNET D1D2 MaxIter= 0
UNET D1D2 ZTol=0.01
UNET D1D2 QTol=0.1
UNET D1D2 MinQTol=1
Write IC File= 0
Write IC File at Fixed DateTime=0
Write IC File at Sim End=0
Echo Input=False
Echo Parameters=False
Echo Output=False
Write Detailed= 0
HDF Write Warmup=0
HDF Write Time Slices=0
HDF Flush=0
HDF Compression= 1
HDF Chunk Size= 1
HDF Spatial Parts= 1
HDF Use Max Rows=0
HDF Fixed Rows= 1
Calibration Method= 0
Calibration Iterations= 20
Calibration Max Change=0.05
Calibration Tolerance=0.2
Calibration Maximum=1.5
Calibration Minimum=0.5
Calibration Optimization Method= 1
WQ AD Non Conservative
WQ ULTIMATE=-1
WQ Max Comp Step=1HOUR
WQ Output Interval=15MIN
WQ Output Selected Increments= 0
WQ Output face flow=0
WQ Output face velocity=0
WQ Output face area=0
WQ Output face dispersion=0
WQ Output cell volume=0
WQ Output cell surface area=0
WQ Output cell continuity=0
WQ Output cumulative cell continuity=0
WQ Output face conc=0
WQ Output face dconc_dx=0
WQ Output face courant=0
WQ Output face peclet=0
WQ Output face adv mass=0
WQ Output face disp mass=0
WQ Output cell mass=0
WQ Output cell source sink temp=0
WQ Output nsm pathways=0
WQ Output nsm derived pathways=0
WQ Create Restart=0
WQ Fixed Restart=0
WQ System Summary=0
WQ Write To DSS=0
Sorting and Armoring Iterations= 10
XS Update Threshold= 0.02
Bed Roughness Predictor= 0
Hydraulics Update Threshold= 0.02
Energy Slope Method= 1
Volume Change Method= 1
Sediment Retention Method= 0
Sediment TS Multiplier= 1
Warm Up Method= 0
XS Weighting Method= 0
Number of US Weighted Cross Sections= 1
Number of DS Weighted Cross Sections= 1
Upstream XS Weight=0
Main XS Weight=1
Downstream XS Weight=0
Number of DS XS's Weighted with US Boundary= 1
Upstream Boundary Weight= 1
Weight of XSs Associated with US Boundary= 0
Number of US XS's Weighted with DS Boundary= 1
Downstream Boundary Weight= 0.5
Weight of XSs Associated with DS Boundary= 0.5
Percentile Method= 0
Sediment Output Level= 3
Mass or Volume Output= 0
Output Increment Type= 1
Profile and TS Output Increment= 1
Transport Output Increment 1
XS Output Flag= 0
XS Output Increment= 10
Read HDF5 Sediment Hotstart= 0
Sediment Hotstart Type= 0
Write Gradation File= 0
Read Gradation Hotstart= 0
Write HDF5 File= 1
Write Binary Output= 1
Write DSS Sediment File= 0
DSS Sediment Output Type= 1
SV Curve= 0
Specific Gage Flag= 0
Subcell Erosion Methods= 0
Subcell Deposition Methods= 0
Advection Scheme= 1
Matrix Solver= 0
Implicit Weighting Factor= 1
Maximum Outer Loop Convergence Iterations= 5
Convergence Maximum Absolute= 0.001
Convergence RMSE= 0.0001
Grain Fractions Max Abs Error= 0.001
Max Subgrid Regions= 1
Max Subgrid Length Scale= 3.402823E+38
Initial Layer Thickness= 3.402823E+38
Min Layer Thickness= 3.402823E+38
Max Layer Thickness= 3.402823E+38
Number of Layers= 5

--- RUSHRN3.f01 (steady flow) ---

Flow Title=Flow
Program Version=6.31
Number of Profiles= 1
Profile Names=F01pct
River Rch & RM=RUSHRN3,Main            ,7019
     761
River Rch & RM=RUSHRN3,Main            ,2998
     895
Boundary for River Rch & Prof#=RUSHRN3,Main            , 1
Up Type= 0
Dn Type= 3
Dn Slope=0.01073
DSS Import GetInterval= 0
DSS Import GetPeak= 0
DSS Import FillOption= 0

--- RUSHRN3.g01 (geometry) ---

Geom Title=Geometry
Program Version=6.31

River Reach=RUSHRN3         ,Main
Reach XY= 30
     1620494.635      415849.9031620504.48848303415747.246868266
     1620427.066      415637.394     1620133.686      414893.791
     1619993.998      414832.175     1620019.555      414730.647
      1619925.73      414652.926     1619908.575      414579.755
     1619696.067       414449.17     1619673.311      414373.549
      1619596.64      414372.499     1619539.224      414254.867
     1619556.028      414149.488     1619495.112      413968.489
     1619682.413      413732.174     1619692.566      413629.596
     1619631.999      413502.861     1619771.337      413286.152
     1619752.782      413155.917     1619905.074      412747.005
       1619817.2      412615.019     1619903.673      412475.681
     1619554.278      412095.127     1619381.681      411796.145
     1619238.142      411695.318     1618964.017      411024.535
     1618856.187      410877.494     1618803.673      410645.381
     1618661.884      410509.194      1618388.62      410109.869

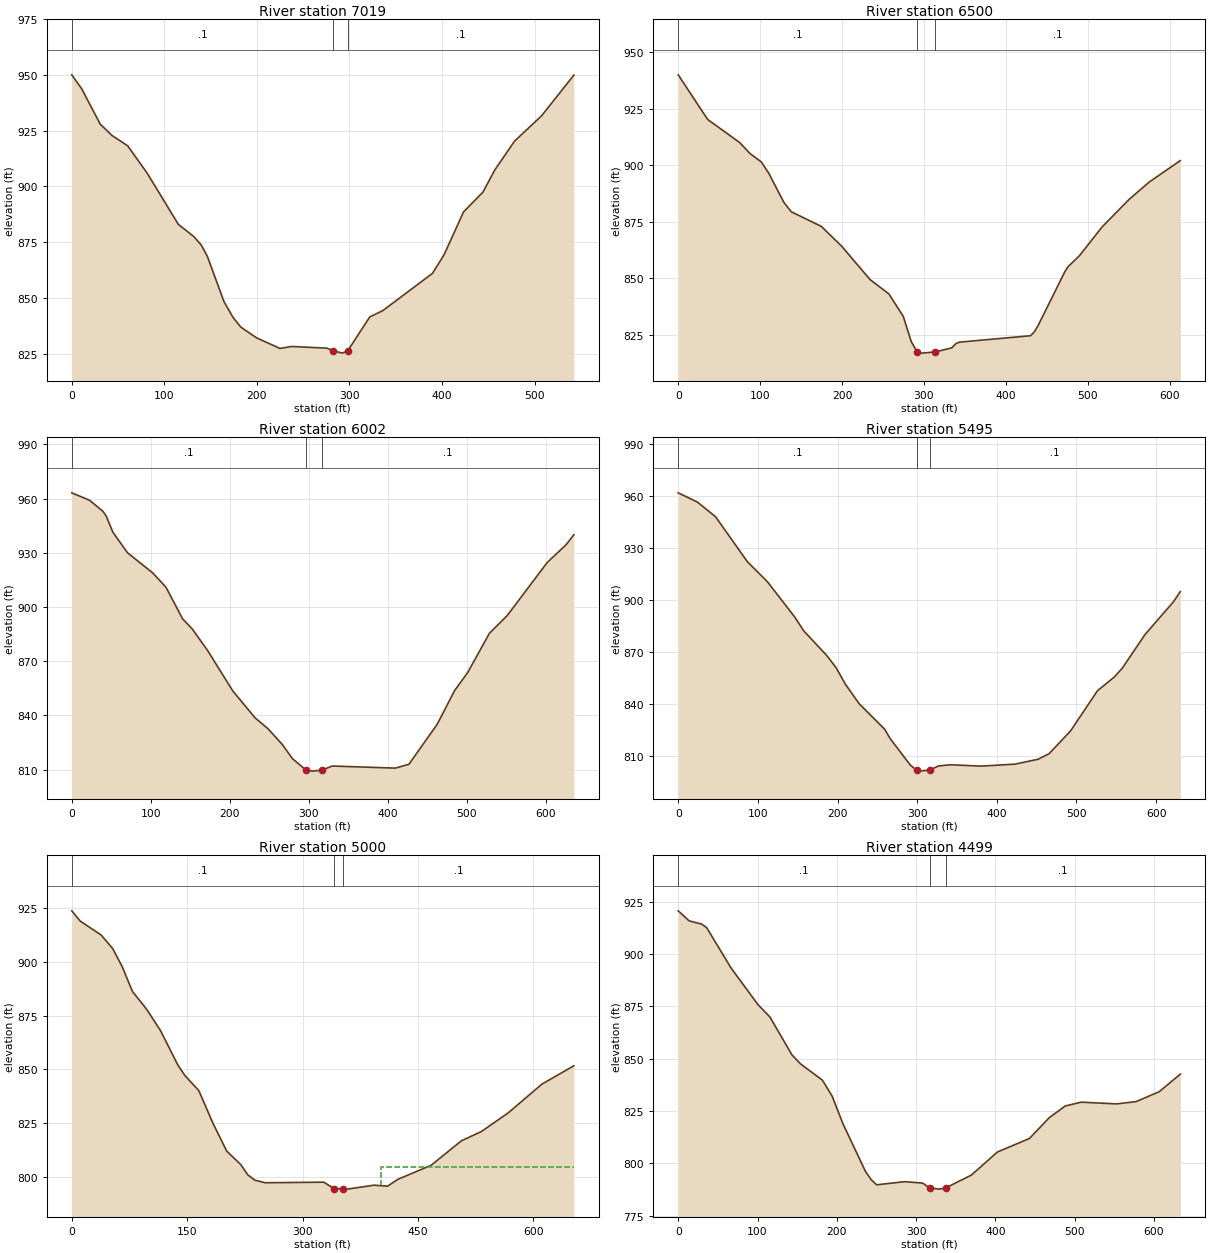
Type RM Length L Ch R = 1 ,7019    ,520.3,518.9,517.1
XS GIS Cut Line= 2
1620769.33307665415744.1478768491620255.05280873415916.949887793
#Sta/Elev= 30
       0  950.08    10.7  943.83    30.8  927.94    43.5  922.86    60.4  918.25
    81.5  905.96   115.2  882.97   132.1  877.46   140.2  873.57   146.6  868.55
   164.5  848.32   174.3  841.25   182.7  836.89   199.6  832.12   224.9  827.34
   237.6  828.23   275.6  827.47   282.7   826.3   292.4  825.24   298.2   826.3
     322  841.48   336.1  844.32   389.8  861.04   402.2  869.29   423.3  888.58
   444.4  897.52     457  907.35   478.4  920.32   507.7  931.73   542.5  949.95
#Mann= 3 ,-1,0
       0      .1       0   282.7    .045       0   298.2      .1       0
Bank Sta=282.7,298.2
XS Rating Curve= 0 ,0
Exp/Cntr(USF)=0,0
Exp/Cntr=0.3,0.1

Type RM Length L Ch R = 1 ,6500    ,495,498.3,498.7
XS GIS Cut Line= 6
 1620608.4791235415214.9467710111620384.71087025415340.402228758
1620296.85245018415388.2226711661620230.82928826415423.746550262
1620154.76710442 415466.978419171620076.18819334415518.435665339
#Sta/Elev= 30
       0   939.9    35.9  920.18    74.9     910    87.6  905.11   101.4   901.4
   110.5  896.43   128.9  883.55     138  879.35   174.7  872.89   199.4  864.18
   234.3  849.33   257.2  843.04   274.8  833.08   284.5  821.93  291.84 817.401
   297.7  816.85  314.05817.4024   333.8  819.16   339.2  821.12   343.7  821.72
   430.1  824.54   434.7   826.2   439.3  828.99   472.2  852.98   476.1  855.12
   489.9  859.95   517.5  872.63   550.5  884.82   574.8  892.43     613  901.99
#Mann= 3 ,-1,0
       0      .1       0  291.84    .045       0  314.05      .1       0
Bank Sta=291.84,314.05
XS Rating Curve= 0 ,0
Exp/Cntr(USF)=0,0
Exp/Cntr=0.3,0.1

Type RM Length L Ch R = 1 ,6002    ,506.5,507,499.9
XS GIS Cut Line= 6
1620433.56346284414821.2759704291620189.68829443414899.945760593
1620095.28297143414933.5683967621620029.35495368414982.845857263
1619959.89347842 415048.442182751619888.15477675415119.504704669
#Sta/Elev= 30
       0  963.14    22.5  959.04    39.3  952.96    43.6  950.31      52  941.37
    70.5  929.99   102.4  918.84   119.2  910.92   140.2  893.46   152.8  887.63
   172.2  875.68   203.9  853.42   232.1  838.59   248.4  832.58   266.4  823.89
   279.2  816.07   296.1  809.82   304.6  809.15   317.2  809.76   329.5  811.98
   409.4  810.82   426.6  812.94   462.5  835.14   484.5  853.78     501  863.72
   528.5  885.44   550.9  895.17   601.6  924.59   625.4  934.39   635.3  939.94
#Mann= 3 ,-1,0
       0      .1       0   296.1    .045       0   317.2      .1       0
Bank Sta=296.1,317.2
XS Rating Curve= 0 ,0
Exp/Cntr(USF)=0,0
Exp/Cntr=0.3,0.1

Type RM Length L Ch R = 1 ,5495    ,492.1,494.5,493.1
XS GIS Cut Line= 6
1620126.14281784414364.1144831781619940.11792742414540.349366918
1619858.81789318414602.2357260881619791.41448468414643.955130845
1619716.71351859414699.2394690961619642.73171118414766.195700005
#Sta/Elev= 30
       0  961.77    23.9  956.49    46.9  947.97    86.6  922.18   112.1  910.42
   146.1  890.26   157.6  882.15   186.7  867.83   198.4  860.78     210  851.29
   227.4  840.01   259.2  825.41   266.3  819.88   291.4  804.74   299.2  801.87
   302.8  801.25     316  801.92   326.6   804.2   341.7  804.92   380.4  804.14
   422.8  805.29   451.8  808.09   465.6  811.29   492.5  824.37   526.4  847.62
   547.6  855.56   557.5   860.6   586.2  880.11     622  899.04   630.4   904.8
#Mann= 3 ,-1,0
       0      .1       0   299.2    .045       0     316      .1       0
Bank Sta=299.2,316
XS Rating Curve= 0 ,0
Exp/Cntr(USF)=0,0
Exp/Cntr=0.3,0.1

Type RM Length L Ch R = 1 ,5000    ,489.8,501,507.7
XS GIS Cut Line= 6
  1619857.809365414134.3088404241619765.05462925414183.709004089
1619674.54628009414232.1554295121619596.79413901414274.426998511
1619505.05941434 414314.235645921619269.98934643414416.246596754
#Sta/Elev= 30
       0  923.68      11  918.92    38.2  912.45    53.2  906.16    65.4  897.84
      79  886.18    97.1  878.09   115.3  868.08   137.9  852.06     147  847.22
   165.1  840.22   183.3  825.17   201.4  812.11   219.6  805.87   228.7  801.12
   237.8  798.62   251.5  797.41   327.5  797.68   340.8   794.7   353.1   794.7
     358  794.45   392.9  796.29   410.4  795.82   423.4  798.94     467  805.51
   506.3  816.87   532.5  821.23   567.3  829.89   610.9  843.17   652.5  851.74
#Mann= 3 ,-1,0
       0      .1       0   340.8    .045       0   353.1      .1       0
#XS Ineff= 2 , 0
                          402.08          804.85
Permanent Ineff=
       F       F
Bank Sta=340.8,353.1
XS Rating Curve= 0 ,0
Exp/Cntr(USF)=0,0
Exp/Cntr=0.3,0.1

Type RM Length L Ch R = 1 ,4499    ,493.6,499.4,496.7
XS GIS Cut Line= 6
1619848.56430475414007.132585585 1619753.2091805413962.538514674
1619669.89340226413914.9546203321619605.44143142413875.225041002
1619395.26632684413717.9454999271619318.36129692413664.196919754
#Sta/Elev= 30
       0   920.6    13.7  915.81    29.4  914.29    35.8   912.6    66.7  893.24
   100.5  875.83   115.7  869.86   143.4  851.79   154.4  847.42   181.9  839.68
   194.1  832.06     208  818.67   236.2  796.05   243.9  791.94   250.3  789.68
   285.5  791.18   308.3   790.5     317  788.24     329  787.62  337.58  788.24
   369.8  794.34   402.7  805.38   442.9  811.79     468  821.76   488.1  827.33
   508.2  829.17   553.1  828.35   577.5  829.44   606.7  834.18   633.3  842.57
#Mann= 3 ,-1,0
       0      .1       0     317    .045       0  337.58      .1       0
Bank Sta=317,337.58
XS Rating Curve= 0 ,0
Exp/Cntr(USF)=0,0
Exp/Cntr=0.3,0.1

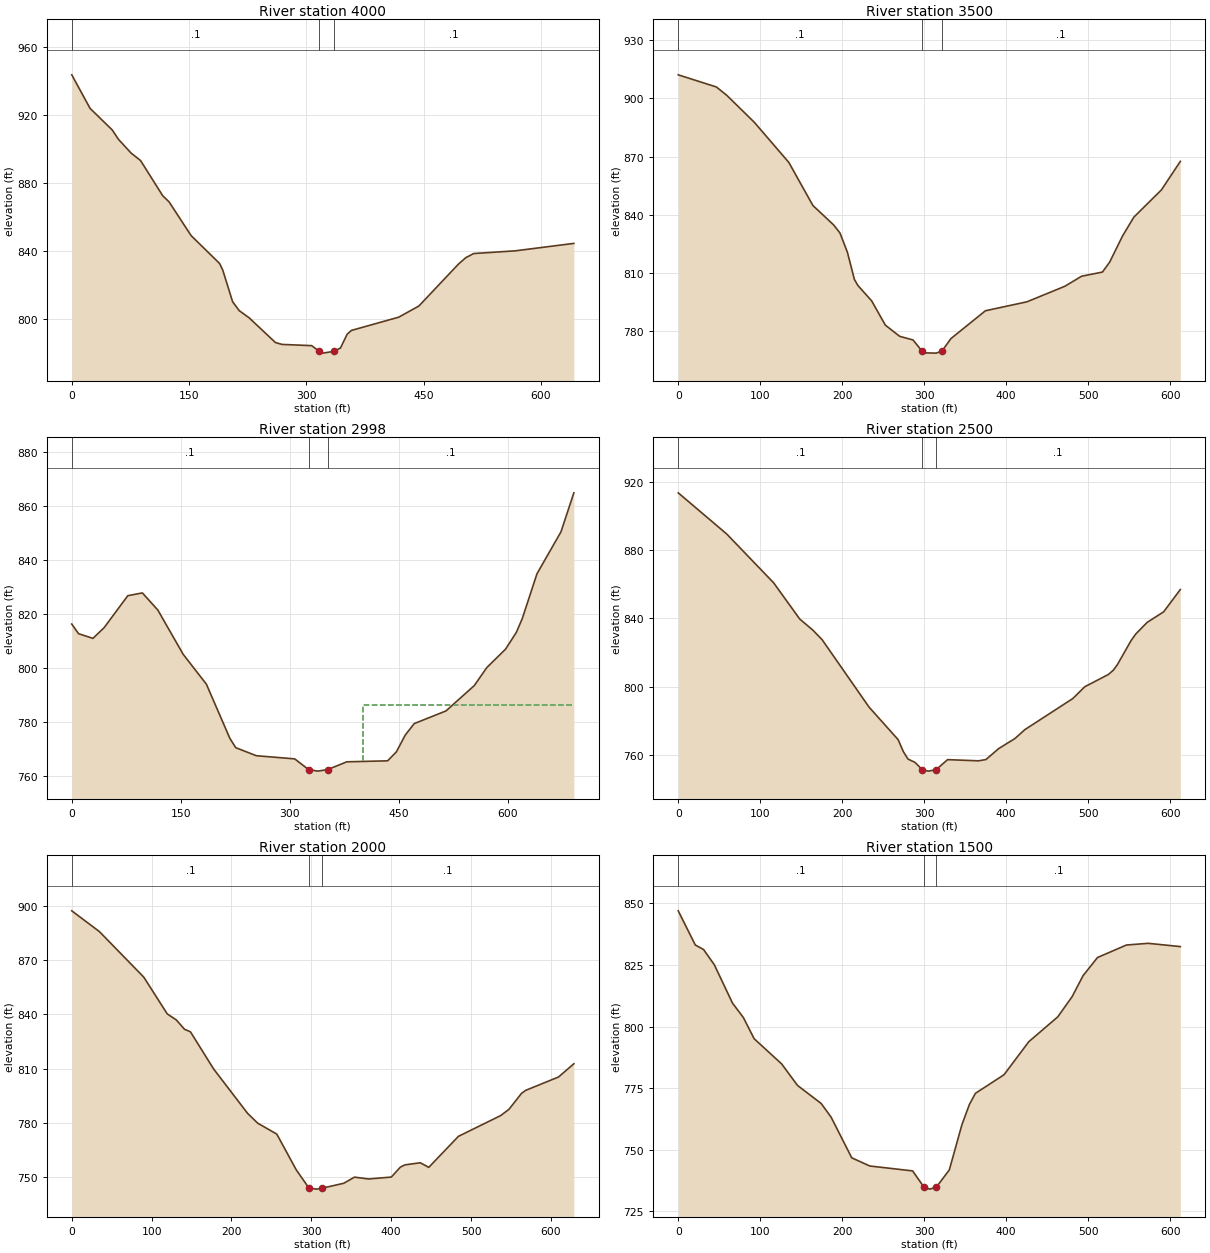
Type RM Length L Ch R = 1 ,4000    ,503.7,499.6,494.7
XS GIS Cut Line= 6
1619983.33568875413531.293970332  1619790.022099413503.540416926
1619711.58327951413477.7917807551619645.60178417413399.525533095
1619514.40683658 413298.286234261619432.26854943413248.186925009
#Sta/Elev= 30
       0  943.82    23.4   924.1    51.7  911.44    59.7  905.91    75.9  897.81
      88  893.42   116.3  872.75   124.4  869.16   152.7  849.27   189.1   832.9
   193.2  828.95   205.7  810.45   214.2  805.15   226.8  800.99   260.5  786.42
   268.9  785.31   306.8  784.59   316.7  781.25   321.4  780.19   335.2  781.25
   343.7  783.19   352.2  791.28   357.7  793.54   418.2  801.33     444  807.89
   494.5  832.49   504.1  836.35   514.1  838.74   567.4  840.34   642.2  844.71
#Mann= 3 ,-1,0
       0      .1       0   316.7    .045       0   335.2      .1       0
Bank Sta=316.7,335.2
XS Rating Curve= 0 ,0
Exp/Cntr(USF)=0,0
Exp/Cntr=0.3,0.1

Type RM Length L Ch R = 1 ,3500    ,489.2,502.4,500.3
XS GIS Cut Line= 6
  1620104.300998413085.1938126681620015.20570375413056.020970762
  1619765.738683412974.3360947521619694.46192268412950.997886837
1619611.30657718412923.7689386761619522.21095484412894.596424833
#Sta/Elev= 30
       0  912.09    46.5  905.84    59.1  901.59    92.8  887.65   134.9  866.99
   164.3  844.78   189.6  834.79   197.3  830.65   206.4  820.69   214.9  806.75
   219.1  803.64   235.9  795.72   252.7  783.17   270.2  777.41   286.4  775.56
  297.36769.8595   301.9   768.9   314.6  768.77  321.83769.8598   332.7  776.27
   374.8   790.6   425.3  795.18   471.6  803.19   492.1  808.38   517.5  810.51
   526.3  815.62     542  829.07   555.8  838.78   589.5  852.86   612.5  867.49
#Mann= 3 ,-1,0
       0      .1       0  297.36    .045       0  321.83      .1       0
Bank Sta=297.36,321.83
XS Rating Curve= 0 ,0
Exp/Cntr(USF)=0,0
Exp/Cntr=0.3,0.1

Type RM Length L Ch R = 1 ,2998    ,518.8,497.6,482.6
XS GIS Cut Line= 6
1620185.20208292412620.9732844231619983.77663276412613.362407252
1619895.96217585412600.6750966761619820.99250951412530.292035341
1619733.26663509412518.8146960881619526.10235126412543.024949506
#Sta/Elev= 30
       0  816.27     9.3  812.72    29.1  810.98    44.5  814.94    77.1  826.77
    97.1  827.79   118.3  821.48   153.2   805.1   185.2  794.01   217.4  774.02
   225.5  770.56   253.8  767.58   306.6  766.41   325.6  762.47   338.4  761.88
  352.14  762.47   378.2  765.32   434.4  765.69   446.5  769.03   458.6   775.2
     471  779.46   514.6  784.14   553.5  793.49   570.9  800.21   596.6     807
   611.4  813.18   619.5  818.25   639.8  834.88   672.8  850.38   690.5  864.81
#Mann= 3 ,-1,0
       0      .1       0   325.6    .045       0  352.14      .1       0
#XS Ineff= 2 , 0
                          401.08          786.48
Permanent Ineff=
       F       F
Bank Sta=325.6,352.14
XS Rating Curve= 0 ,0
Exp/Cntr(USF)=0,0
Exp/Cntr=0.3,0.1

Type RM Length L Ch R = 1 ,2500    ,500.9,500,498.7
XS GIS Cut Line= 6
1619880.27848017411993.2251960931619686.29592851412160.661212921
1619610.59529251412226.001961499 1619553.8201436412275.008097082
1619487.83536743412332.4748456781619418.00939159412395.056085333
#Sta/Elev= 30
       0  913.46    59.2  889.36   116.5  860.77   148.2  839.66   164.1  833.21
   175.5  827.59   232.7  788.19   268.3  769.08   274.7  762.03   280.3  757.75
   288.9  755.79  297.87  751.48     305  750.69   314.4  751.46   328.6  757.41
   366.3  756.71   375.4  757.46   390.7  763.78   410.9  769.81   422.9  774.97
   481.3  793.12   495.9  800.03   524.8  807.23   530.8  809.73   535.6  812.86
   552.6  827.17   558.3  830.96   572.1   837.7   592.2  843.87   612.5   856.9
#Mann= 3 ,-1,0
       0      .1       0  297.87    .045       0   314.4      .1       0
Bank Sta=297.87,314.4
XS Rating Curve= 0 ,0
Exp/Cntr(USF)=0,0
Exp/Cntr=0.3,0.1

Type RM Length L Ch R = 1 ,2000    ,496.1,500,502.8
XS GIS Cut Line= 6
 1619572.9654465411556.6073029191619404.47300135411749.672861665
1619338.72018009411825.0158868431619281.21931084411878.876671508
1619210.16728759411940.5776635861619134.13922442412004.944660842
#Sta/Elev= 30
       0   897.3    34.6  885.83    90.2  860.64   119.6  840.31     131  836.98
   141.2  831.84   148.6  830.45   177.7  809.87   220.3  785.31     233  779.89
   256.8  773.89   281.1  754.17   297.2  743.99   306.7  743.48  313.42  743.98
   340.7  746.72   354.1  750.11   371.9  749.09   400.2  750.15   411.5  755.62
   417.2  756.89   436.5  758.05   447.1  755.51   484.2  772.64   537.1  784.11
   547.6   787.6   563.3  796.43   568.5  798.07   609.6  805.45   628.8  812.77
#Mann= 3 ,-1,0
       0      .1       0   297.2    .045       0  313.42      .1       0
Bank Sta=297.2,313.42
XS Rating Curve= 0 ,0
Exp/Cntr(USF)=0,0
Exp/Cntr=0.3,0.1

Type RM Length L Ch R = 1 ,1500    ,501.3,500.2,496.4
XS GIS Cut Line= 6
1619392.16003384411256.9815898391619159.66148309 411364.72382842
1619068.93003726411406.7696760891619000.88194501411438.304061845
1618921.49201192411475.0936864171618836.43115842411514.511586592
#Sta/Elev= 30
       0  846.96    20.8   833.1    30.9  831.26    44.1  825.02    66.2  809.49
    79.4  803.67    92.6  795.05   126.2   784.8   145.5  776.09   174.4  768.74
   186.5   763.2   211.7  746.68   233.7  743.37   285.9  741.38   299.8  734.79
     307  733.98  314.92   734.8   330.7  741.79   346.1  760.15   355.2  768.34
   362.5  772.86   397.4  780.41   427.7  793.84     463  803.91   480.6  812.16
   493.8   820.6   511.5  828.01   546.7  833.07   573.2  833.77   612.5  832.44
#Mann= 3 ,-1,0
       0      .1       0   299.8    .045       0  314.92      .1       0
Bank Sta=299.8,314.92
XS Rating Curve= 0 ,0
Exp/Cntr(USF)=0,0
Exp/Cntr=0.3,0.1

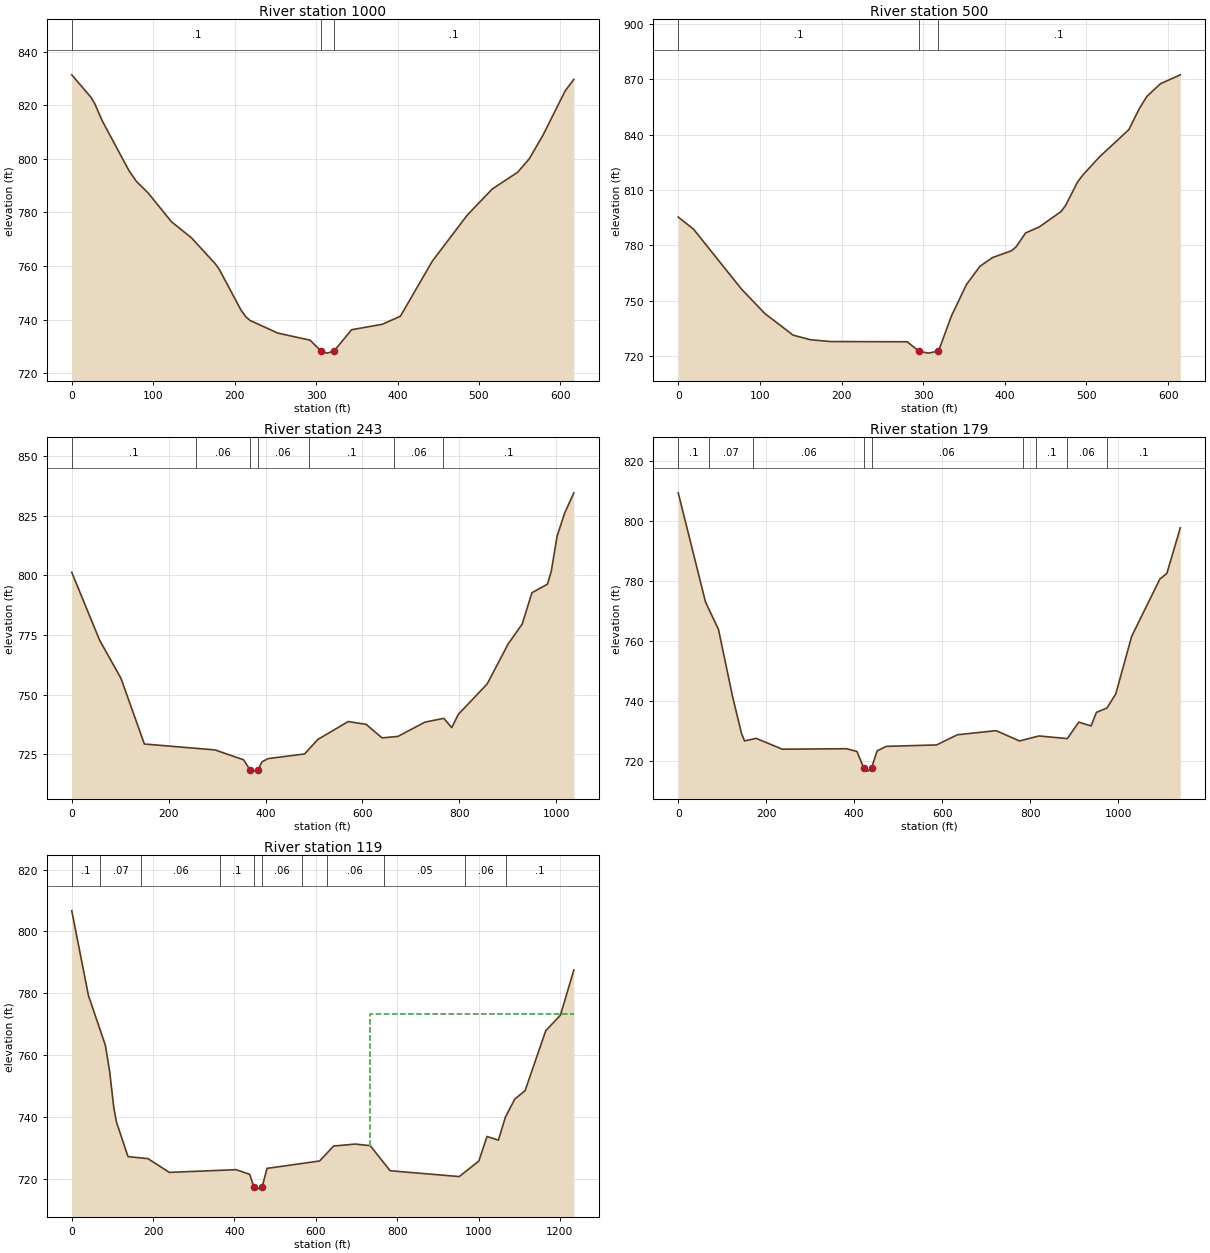
Type RM Length L Ch R = 1 ,1000    ,502.7,499.8,499.8
XS GIS Cut Line= 6
1619144.30193375410757.0075241771619061.60262409410806.340102673
1618988.76320285410857.3662473411618933.94277443410908.591866672
1618803.97715509411025.7842175961618672.43214259411150.447354093
#Sta/Elev= 30
       0  831.32    23.5  822.96    28.2  820.57    37.5   814.1    70.1  795.65
    79.4  791.54    93.4  787.36   122.5  776.47     147  770.49   176.3  760.78
   181.1  758.75   207.7  743.59   213.5  741.08     219  739.64     253  734.94
   292.7  732.29   305.9  728.26   313.8  727.46   322.1  728.26   343.6  736.19
   381.3  738.23   403.5  741.22   442.8  761.82   485.8  779.04   516.3  788.71
   547.5  794.96   561.8  800.01   578.4  808.66   605.9  825.37   616.5  829.62
#Mann= 3 ,-1,0
       0      .1       0   305.9    .045       0   322.1      .1       0
Bank Sta=305.9,322.1
XS Rating Curve= 0 ,0
Exp/Cntr(USF)=0,0
Exp/Cntr=0.3,0.1

Type RM Length L Ch R = 1 ,500     ,252.5,257,260.3
BEGIN DESCRIPTION:
Structure 1 XS 4
END DESCRIPTION:
XS GIS Cut Line= 6
1618889.02750993410300.4615212531618823.56373009410369.504034087
 1618762.4710045 410433.526871921618708.33200517410485.451636836
1618635.95813417410554.4587166761618450.50049984410731.290712088
#Sta/Elev= 30
       0  795.31    18.8  788.71    77.3  756.37   105.9  743.09   140.7  731.35
     162  728.83   186.9  727.86   280.5  727.74   294.9  722.57   306.3  721.59
   317.6   722.6   320.4  724.65   334.5  741.61   352.9  758.68   369.5  768.63
   384.9  773.36   408.2  777.04   413.8  779.17   425.4  786.68   442.1  789.94
     469  798.34   474.5  801.67   489.2   814.4   495.8  818.22   515.6  827.76
   551.9  842.68   564.5  853.91     574   860.7   590.6  867.52   614.9  872.35
#Mann= 3 ,-1,0
       0      .1       0   294.9    .045       0   317.6      .1       0
Bank Sta=294.9,317.6
XS Rating Curve= 0 ,0
Exp/Cntr(USF)=0,0
Exp/Cntr=0.3,0.1

Type RM Length L Ch R = 1 ,243     ,64.4,63.8,65.6
BEGIN DESCRIPTION:
Structure 1 XS 3
END DESCRIPTION:
XS GIS Cut Line= 6
1618881.41980772410265.2049347221618728.90305255410251.546717841
1618666.30289185410264.066749981 1618437.5277591410342.601497046
1618109.73055396 410417.721689891618117.69784714410659.016854784
#Sta/Elev= 30
       0  801.21    57.5  772.82   101.7  756.79   149.9  729.35   295.6  726.89
   354.9  722.73  367.91  718.52     376     718   384.4  718.51   392.9  721.92
   405.5  723.25   480.7  725.18   507.9  731.24   570.8  738.76   607.8  737.58
   640.7  731.91   673.5  732.54     729   738.5   768.1   740.1   784.5  736.21
     798  741.73   857.7  754.52   900.9  771.21   930.1  779.63   950.1  792.69
   982.1  796.26   990.1  801.75  1002.1  816.46  1018.1  826.24  1036.6   834.5
#Mann= 7 ,-1,0
       0      .1       0  256.97     .06       0  367.91    .045       0
   384.4     .06       0  488.85      .1       0  666.27     .06       0
  766.52      .1       0
Bank Sta=367.91,384.4
XS Rating Curve= 0 ,0
Exp/Cntr(USF)=0,0
Exp/Cntr=0.3,0.1

Type RM Length L Ch R = 1 ,179     ,60.3,60.6,62.3
BEGIN DESCRIPTION:
Structure 1 XS 2
END DESCRIPTION:
XS GIS Cut Line= 6
1618893.93983986410251.5467178411618661.78849138410206.404274426
 1618557.7020954410241.0997397531618438.00274002410275.795205081
1618033.80056895410362.5338683991618048.27534361 410618.96701177
#Sta/Elev= 30
       0  809.33    62.1  772.92    91.5  763.85   123.5  741.49     144   729.1
   150.8  726.72   177.1  727.58   236.5  723.96   382.6  724.12   406.2  723.21
   421.3  717.82   431.2  716.66   439.5   717.8     452  723.39   472.8  724.91
   587.2  725.38   634.4  728.77   722.4  730.14   775.6  726.71   819.9  728.37
   884.3  727.49   910.3  732.97   938.3  731.71   950.4  736.22   974.4  737.69
   994.4  742.36  1030.5  761.53  1094.6  780.61  1110.6  782.53  1141.1  797.69
#Mann= 9 ,-1,0
       0      .1       0      70     .07       0     170     .06       0
   421.3    .045       0   439.5     .06       0  783.52     .05       0
  813.52      .1       0  883.52     .06       0  974.25      .1       0
Bank Sta=421.3,439.5
XS Rating Curve= 0 ,0
Exp/Cntr(USF)=0,0
Exp/Cntr=0.3,0.1

Type RM Length L Ch R = 1 ,119     ,,,
BEGIN DESCRIPTION:
Structure 1 XS 1
END DESCRIPTION:
XS GIS Cut Line= 6
1618892.80165512  410239.02668571618662.47636028410200.534393212
1618616.17913667 410209.325641091618520.61524512410196.913850318
1617973.14838515410317.5614327651617995.91207995410613.489465182
#Sta/Elev= 30
       0  806.64      41  779.28    82.7  763.12    93.1  754.72   103.5  742.86
   110.2  738.23   138.3  727.16   187.2  726.52     240  722.06     404  722.94
   437.6  721.43   447.5  717.38   455.4  716.65  468.16  717.38     480  723.36
   609.4  725.75   643.8  730.59     697  731.22   733.9   730.7   782.7   722.6
   952.7  720.71  1000.8  725.72  1020.9  733.67  1048.9  732.48  1066.1  739.94
  1089.1  745.75  1114.5  748.49  1165.3  767.88  1201.4  772.89  1234.4   787.5
#Mann= 11 ,-1,0
       0      .1       0      70     .07       0     170     .06       0
  363.81      .1       0   447.5    .045       0  468.16     .06       0
  567.04      .1       0  627.04     .06       0  767.04     .05       0
  967.64     .06       0 1067.64      .1       0
#XS Ineff= 2 , 0
                          733.11           773.4
Permanent Ineff=
       F       F
Bank Sta=447.5,468.16
XS Rating Curve= 0 ,0
Exp/Cntr(USF)=0,0
Exp/Cntr=0.3,0.1
LCMann Table=0

Chan Stop Cuts=-1
Use User Specified Reach Order=0
Composite Channel Slope=5